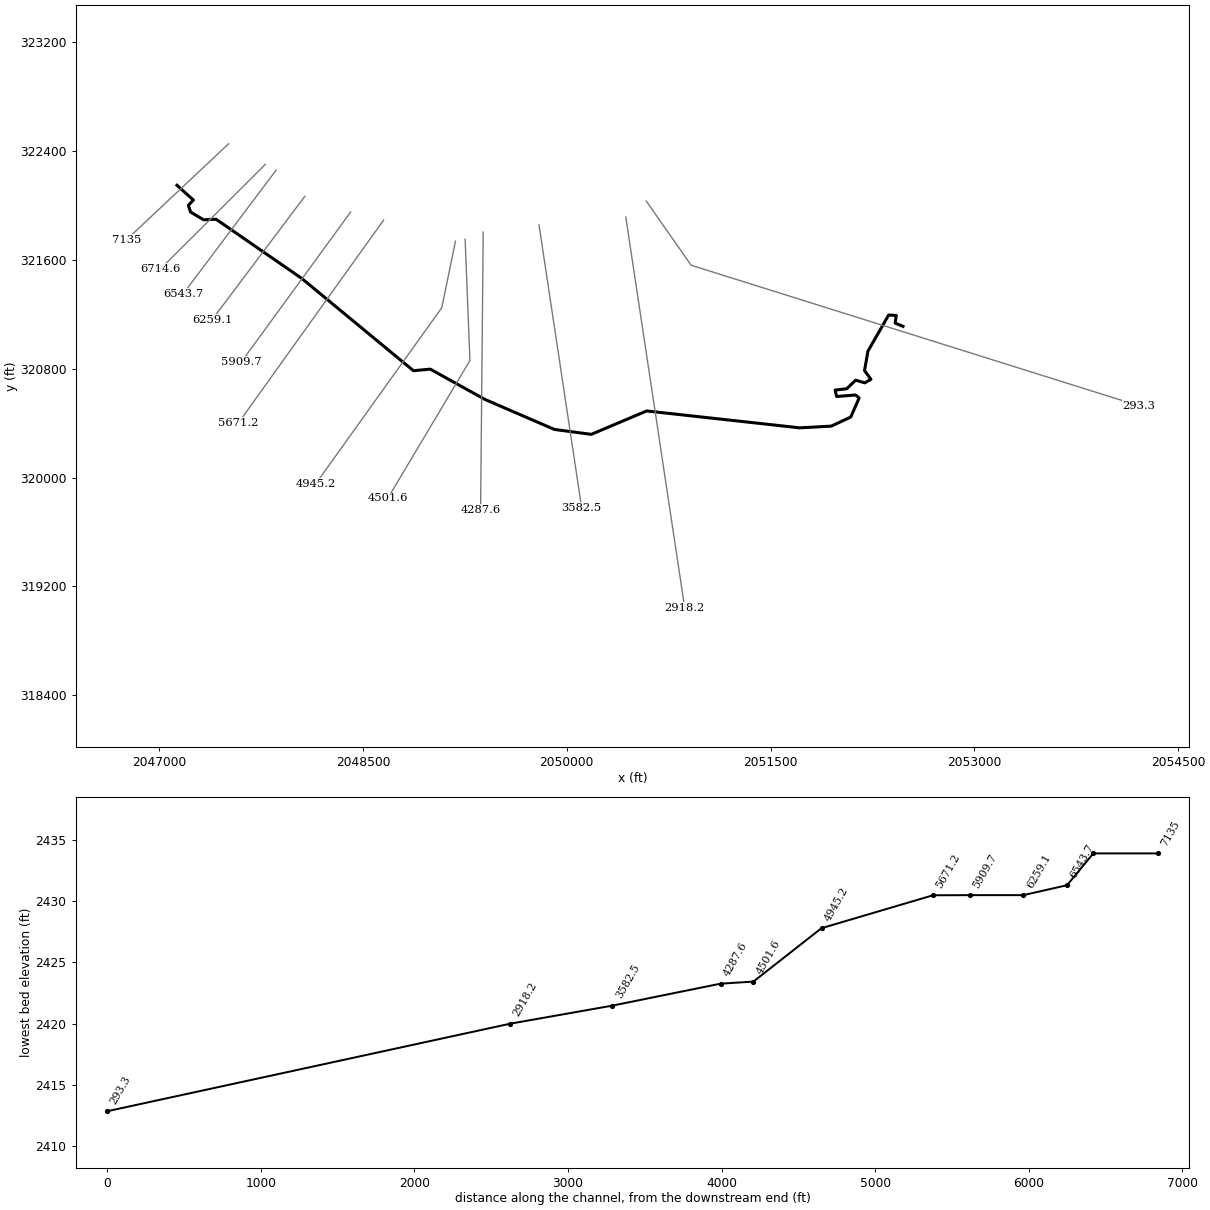
--- EagleBr.prj (project) ---

Proj Title=EagleBr
Current Plan=p01
Default Exp/Contr=0,0
English Units
Geom File=g01
Flow File=f01
Plan File=p01
BEGIN DESCRIPTION:
END DESCRIPTION:
DSS Export Rating Curves= 0
DSS Export Rating Curve Sorted= 0
DSS Export Volume Flow Curves= 0
DXF OffsetX= 0
DXF OffsetY= 0
DXF ScaleX= 0
DXF ScaleY= 0

--- EagleBr.p01 (plan) ---

Plan Title=Floodplain
Program Version=4.00
Geom File=g01
Flow File=f01
K Sum by GR=0
Std Step Tol=0.01
Critical Tol=0.01
Num of Std Step Trials=20
Max Error Tol=0.3
Flow Tol Ratio=0.001
Split Flow NTrial=30
Split Flow Tol=0.02
Split Flow Ratio=0.02
Log Output Level=0
Friction Slope Method=1
Unsteady Friction Slope Method=2
Unsteady Bridges Friction Slope Method=1
Global Log Level=0
CheckData=False
Run HTab=0
Run UNet=0
Run PostProcess=0
UNET Theta=0
UNET Theta Warmup=0
UNET ZTol=0
UNET ZSATol=0
UNET MxIter=0
UNET MaxInSteps=0
UNET DtIC=0
UNET DtMin=0
UNET MaxCRTS=0
UNET WFStab=0
UNET SFStab=0
UNET WFX=0
UNET SFX=0
UNET DSS MLevel=0
UNET DZMax Abort=0
UNET Convert EG Bridges=0
UNET Use Existing IB Tables=0
UNET Froude Limit=0
UNET Froude Power=0
Write IC File=0
Echo Input=False
Echo Output=False
Write Detailed=0

--- EagleBr.f01 (steady flow) ---

Flow Title=NFF Regression Equation
Program Version=4.00
Number of Profiles=1
Profile Names=P100yr
River Rch & RM=EagleBr,Main      ,7135
562.1327
River Rch & RM=EagleBr,Main      ,4287.6
608.2601
River Rch & RM=EagleBr,Main      ,3582.5
686.4870
River Rch & RM=EagleBr,Main      ,293.3
722.8619
Boundary for River Rch & Prof#=EagleBr,Main      ,1
Up Type=0
Dn Type=3
Dn Slope=0.002285

--- EagleBr.g01 (geometry) ---

Geom Title=USGS 10m DEM
Program Version=4.10

River Reach=EagleBr         ,Main
Reach XY= 30
     2047130.347       322148.67     2047251.679      322039.718
     2047214.537      322001.338     2047230.632      321951.814
     2047325.965      321894.862     2047418.821      321898.576
     2048049.008      321463.801     2048871.099      320785.329
     2048994.907      320796.884     2049397.699      320574.028
     2049908.593       320353.66     2050180.238      320317.441
     2050587.705      320489.483     2051713.749      320365.411
      2051946.51      320377.791     2052090.128      320444.648
     2052152.032      320584.552     2052124.794      320606.838
     2051986.129      320595.695     2051974.986      320642.742
     2052060.414      320652.647     2052126.032      320715.789
     2052192.889       320695.98     2052238.699       320721.98
     2052191.651       320786.36     2052216.413       320928.74
      2052369.11      321194.723     2052425.237      321191.422
     2052416.983      321135.295     2052474.734       321111.26

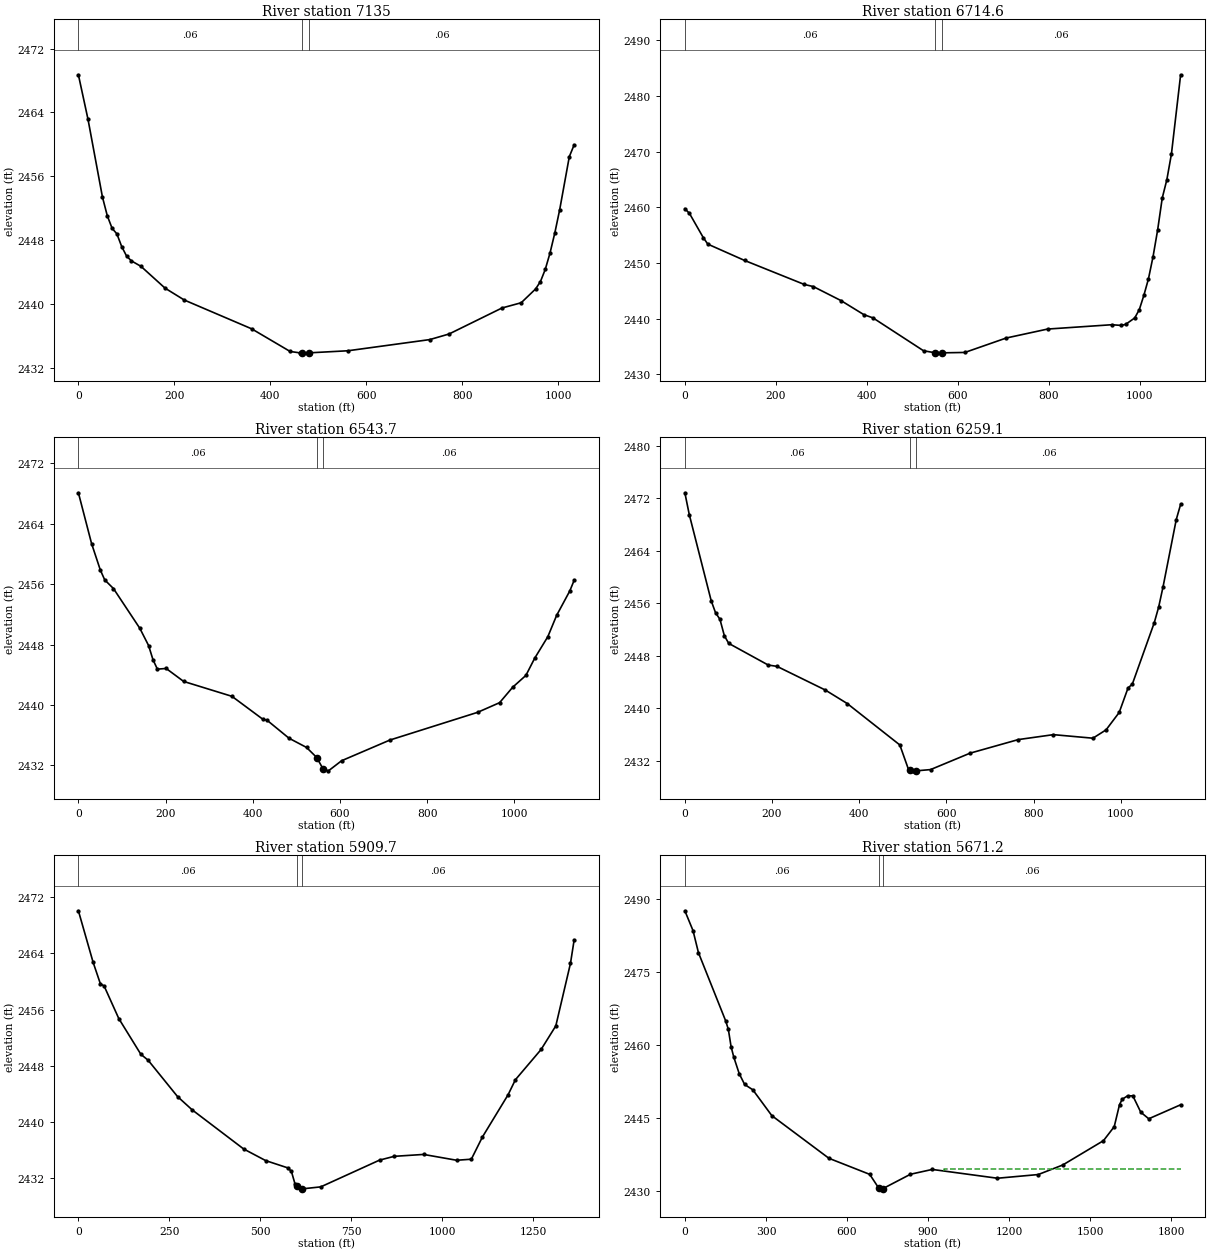
Type RM Length L Ch R = 1 ,7135    ,423.3,420.5,394.2
XS GIS Cut Line= 2
     2047510.676      322453.314     2046757.587      321746.424
#Sta/Elev= 30
       0 2468.72    20.1 2463.12    50.1  2453.4    60.2 2451.05    70.2 2449.48
    80.2 2448.78    90.2 2447.19   100.3 2446.01   110.3  2445.4   130.4 2444.71
   180.5 2441.98   220.6 2440.49     361 2436.88   441.2 2434.04   461.3 2433.87
   465.9 2433.87   480.9 2433.87   561.6 2434.13     732 2435.53   772.2 2436.23
   882.5 2439.49   922.6 2440.15   952.6 2441.88   962.7 2442.81   972.7 2444.33
   982.7  2446.4   992.8 2448.95  1002.8 2451.83  1022.8 2458.46  1032.9 2459.94
#Mann= 3 , 0 , 0
       0     .06       0   465.9    .045       0   480.9     .06       0
Bank Sta=465.9,480.9
XS Rating Curve= 0 ,0
Exp/Cntr=0.3,0.1

Type RM Length L Ch R = 1 ,6714.6  ,165.1,170.7,186.7
XS GIS Cut Line= 2
      2047781.28      322302.346      2047009.21      321533.243
#Sta/Elev= 30
       0 2459.76    10.1 2458.92    40.4 2454.58    50.4  2453.4   131.2 2450.47
   262.4 2446.16   282.5 2445.77   343.1 2443.26   393.5 2440.73   413.7 2440.14
   524.7 2434.24   550.5 2433.88     555 2433.87   565.5 2433.87   615.5 2433.94
   706.3 2436.53   797.2 2438.14   938.4 2438.92   958.6  2438.8   968.7 2438.97
   988.9 2440.14     999 2441.64    1009  2444.2  1019.1 2447.17  1029.2 2451.16
  1039.3 2455.96  1049.4 2461.68  1059.5 2464.97  1069.6  2469.6  1089.8 2483.82
#Mann= 3 , 0 , 0
       0     .06       0   550.5    .045       0   565.5     .06       0
Bank Sta=550.5,565.5
XS Rating Curve= 0 ,0
Exp/Cntr=0.3,0.1

Type RM Length L Ch R = 1 ,6543.7  ,284.6,284.6,284.6
XS GIS Cut Line= 2
     2047861.016       322260.33     2047177.175      321351.666
#Sta/Elev= 30
       0 2468.11    30.2 2461.39    50.3 2457.88    60.4 2456.57    80.5 2455.42
   140.9 2450.16     161 2447.88   171.1    2446   181.2 2444.75   201.3 2444.84
   241.5 2443.12   352.2 2441.15   422.7 2438.13   432.8 2437.98   483.1  2435.6
   523.3 2434.38   546.8 2433.04   561.8 2431.47   573.6 2431.28   603.8 2432.62
   714.6 2435.36   915.8 2439.03   966.2 2440.31   996.3 2442.36  1026.5 2443.92
  1046.7  2446.2  1076.8 2449.05    1097 2451.87  1127.2 2455.11  1137.2 2456.52
#Mann= 3 , 0 , 0
       0     .06       0   546.8    .045       0   561.8     .06       0
Bank Sta=546.8,561.8
XS Rating Curve= 0 ,0
Exp/Cntr=0.3,0.1

Type RM Length L Ch R = 1 ,6259.1  ,349.2,349.5,349.8
XS GIS Cut Line= 2
     2048072.062      322067.672     2047388.221      321159.008
#Sta/Elev= 30
       0 2472.81    10.1  2469.5    60.4 2456.37    70.4 2454.54    80.5 2453.54
    90.6 2451.04   100.6 2449.88   191.2 2446.58   211.3 2446.38     322 2442.78
   372.4 2440.72   493.1 2434.41   513.3 2430.62   515.5 2430.59   523.3 2430.47
   530.5 2430.47   563.6 2430.66   654.2 2433.16   764.9 2435.23   845.4 2435.98
     936 2435.44   966.2 2436.71   996.3 2439.36  1016.5 2443.08  1026.5 2443.69
  1076.8 2453.04  1086.9 2455.43    1097 2458.53  1127.2 2468.74  1137.2 2471.05
#Mann= 3 , 0 , 0
       0     .06       0   515.5    .045       0   530.5     .06       0
Bank Sta=515.5,530.5
XS Rating Curve= 0 ,0
Exp/Cntr=0.3,0.1

Type RM Length L Ch R = 1 ,5909.7  ,238.3,238.5,238.7
XS GIS Cut Line= 2
     2048409.224      321952.019      2047605.98      320851.936
#Sta/Elev= 30
       0 2470.07    40.4 2462.74    60.5 2459.66    70.6 2459.37     111 2454.72
   171.5 2449.64   191.7 2448.78   272.4 2443.61   312.8 2441.71     454 2436.15
   514.6 2434.49   575.1 2433.46   585.2 2432.96   595.3 2431.14   599.6 2430.88
   614.6 2430.48   615.5 2430.47   665.9 2430.75   827.4 2434.56   867.7  2435.1
   948.4 2435.37  1039.2 2434.54  1079.6 2434.69  1109.9 2437.84  1180.5 2443.86
  1200.7 2446.01  1271.3 2450.32  1311.7 2453.68    1352 2462.59  1362.1 2465.93
#Mann= 3 , 0 , 0
       0     .06       0   599.6    .045       0   614.6     .06       0
Bank Sta=599.6,614.6
XS Rating Curve= 0 ,0
Exp/Cntr=0.3,0.1

Type RM Length L Ch R = 1 ,5671.2  ,726,726,726
XS GIS Cut Line= 3
     2048651.465      321892.365     2047737.717      320617.232
     2047583.178      320401.572
#Sta/Elev= 30
       0 2487.65    30.2 2483.57    50.3 2479.03   150.8 2465.03   160.9 2463.26
     171  2459.7     181 2457.55   201.1 2454.15   221.2 2451.92   251.4 2450.83
   321.8 2445.51     533 2436.74   683.8 2433.44   716.4 2430.68     724 2430.46
   731.4 2430.47   834.6 2433.46   915.1 2434.45  1156.4 2432.64  1307.3  2433.4
  1397.8 2435.36  1548.6 2440.37  1588.4 2443.25    1608 2447.79  1617.9 2448.88
  1637.5 2449.58  1657.2 2449.59  1686.6 2446.22  1716.1 2444.87    1834 2447.75
#Mann= 3 , 0 , 0
       0     .06       0   716.4    .045       0   731.4     .06       0
#XS Ineff= 2 , 0
                          960.39         2434.59
Permanent Ineff=
       F       F
Bank Sta=716.4,731.4
XS Rating Curve= 0 ,0
Exp/Cntr=0.3,0.1

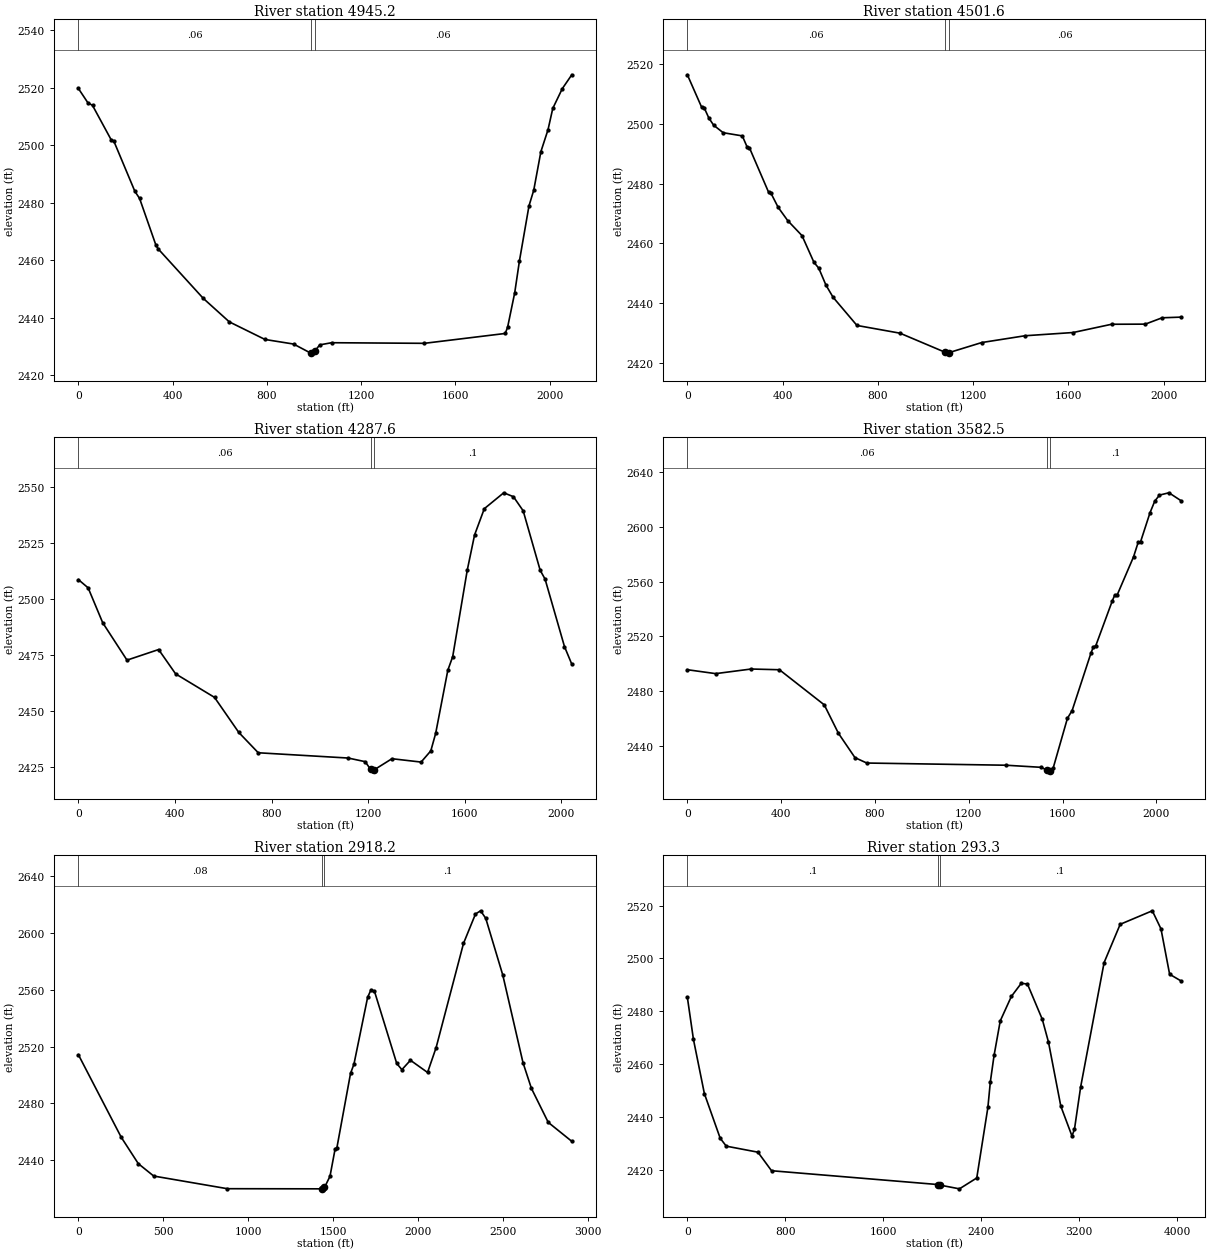
Type RM Length L Ch R = 1 ,4945.2  ,442.1,443.6,445.2
XS GIS Cut Line= 3
     2049180.686       321737.76     2049080.061      321248.846
     2048151.434      319952.949
#Sta/Elev= 30
       0 2519.75    39.9 2514.82    59.9 2513.86   139.8 2501.79   149.8 2501.54
   239.6 2483.97   259.6  2481.5   329.4 2465.13   339.4 2463.86   529.4 2446.76
   640.4 2438.55   791.8 2432.43   912.9 2430.84   983.5 2427.78     988 2427.86
    1003 2428.38  1023.9 2430.55  1074.3  2431.3  1467.8 2431.09  1810.9 2434.52
    1821 2436.65  1851.3  2448.7  1871.4 2459.83  1911.8 2478.91    1932 2484.37
  1962.3 2497.78  1992.5 2505.39  2012.7 2512.81  2053.1 2519.69  2093.4 2524.52
#Mann= 3 , 0 , 0
       0     .06       0     988    .045       0    1003     .06       0
Bank Sta=988,1003
XS Rating Curve= 0 ,0
Exp/Cntr=0.3,0.1

Type RM Length L Ch R = 1 ,4501.6  ,201,213.9,226.8
XS GIS Cut Line= 4
     2049251.733      321752.021     2049286.988      320860.031
     2048696.939      319871.719     2048682.688       319847.85
#Sta/Elev= 30
       0 2516.34    60.2 2505.46    70.2 2505.39    90.3 2501.88   110.3  2499.5
   150.4 2496.98   230.7 2495.92   250.8 2492.24   260.8 2491.92     341 2477.11
   351.1 2476.75   381.2 2472.05   421.3 2467.62   481.4 2462.59   531.6 2453.65
   551.7 2451.73   581.8 2446.07   611.8    2442   712.1 2432.58   892.7    2430
  1082.6 2423.61  1094.6 2423.43  1097.6 2423.48    1236 2426.87  1417.7 2429.14
  1619.7 2430.22  1781.2 2432.98  1922.6 2433.02  1993.2 2435.14  2071.5 2435.36
#Mann= 3 , 0 , 0
       0     .06       0  1082.6    .045       0  1097.6     .06       0
Bank Sta=1082.6,1097.6
XS Rating Curve= 0 ,0
Exp/Cntr=0.3,0.1

Type RM Length L Ch R = 1 ,4287.6  ,752.7,704.8,741.7
XS GIS Cut Line= 2
     2049384.793      321804.686     2049365.453      319761.446
#Sta/Elev= 30
       0 2508.56    40.3 2504.89   100.7 2489.32   201.3 2472.64   332.2 2477.37
   402.6 2466.52   563.7 2456.03   664.3 2440.38   744.9 2431.32  1117.3 2428.97
  1187.8 2427.35  1209.8 2423.93    1218 2423.26  1224.8  2423.7  1298.5 2428.67
  1419.3 2427.17  1459.5 2432.18  1479.6 2439.98    1530 2468.17  1550.1 2474.19
  1610.5 2512.84  1640.7 2528.48    1681  2540.2  1761.5  2547.3  1801.8 2545.54
    1842 2539.25  1912.5  2512.7  1932.6 2508.81  2013.1 2478.67  2043.3 2470.84
#Mann= 3 , 0 , 0
       0     .06       0  1209.8    .045       0  1224.8      .1       0
Bank Sta=1209.8,1224.8
XS Rating Curve= 0 ,0
Exp/Cntr=0.3,0.1

Type RM Length L Ch R = 1 ,3582.5  ,664.5,664.6,664.6
XS GIS Cut Line= 2
      2049795.58       321856.81     2050109.649      319776.608
#Sta/Elev= 30
       0 2495.54   120.8 2492.67   271.8 2496.05   392.6 2495.52   583.8  2469.8
   644.2 2448.97   714.7 2431.14     765 2427.19  1358.9 2425.58  1509.9 2424.03
  1531.4 2422.04  1540.1 2421.47  1546.4 2421.58  1560.2 2423.72  1620.6 2459.95
  1640.7 2465.65  1721.3 2507.89  1731.3 2512.22  1741.4 2513.06  1811.9 2545.95
  1821.9 2550.02    1832 2549.99  1902.5  2578.2  1922.6    2589  1932.7 2589.36
  1972.9  2610.6    1993 2619.01  2013.2 2623.44  2053.4 2625.14  2103.8 2619.48
#Mann= 3 , 0 , 0
       0     .06       0  1531.4    .045       0  1546.4      .1       0
Bank Sta=1531.4,1546.4
XS Rating Curve= 0 ,0
Exp/Cntr=0.3,0.1

Type RM Length L Ch R = 1 ,2918.2  ,2600.4,2623.6,2643.6
XS GIS Cut Line= 3
      2050434.18      321915.531      2050804.45      319463.092
     2050868.079       319041.65
#Sta/Elev= 30
       0 2514.28   252.1  2456.3   352.9  2437.7   443.6    2429   877.2  2420.1
  1431.7    2420  1434.7 2420.02  1449.7 2420.96  1482.1 2428.85  1512.3 2448.11
  1522.4 2448.68  1603.1 2501.16  1623.2 2507.67  1703.9 2554.72  1724.1 2560.03
  1744.2 2558.82  1875.3 2508.12  1905.6  2503.8    1956 2510.39  2056.8 2501.82
  2107.2  2519.3  2268.5 2592.55  2339.1 2613.22  2369.3 2615.49  2399.6 2610.17
  2500.1 2570.21    2619  2508.7  2668.6 2490.63  2767.7 2466.73  2906.4  2453.4
#Mann= 3 , 0 , 0
       0     .08       0  1434.7    .045       0  1449.7      .1       0
Bank Sta=1434.7,1449.7
XS Rating Curve= 0 ,0
Exp/Cntr=0.3,0.1

Type RM Length L Ch R = 1 ,293.3   ,313.8,293.1,263.9
XS GIS Cut Line= 3
     2050584.734      322032.734       2050915.4      321560.659
     2054210.226      320527.997
#Sta/Elev= 30
       0  2485.3    49.7 2469.38   139.1 2448.87   268.3 2431.99     318 2429.01
   576.4 2426.73   687.4 2419.72  2047.1 2414.49  2062.1 2414.29    2222 2412.87
  2363.4 2416.98  2454.2 2443.65  2474.4 2453.38  2504.7 2463.33  2555.2 2476.38
  2646.1 2485.64  2726.8 2490.59  2777.3 2490.32  2898.5 2476.97    2949 2468.37
  3049.9 2444.11  3140.8 2432.87    3161 2435.31  3211.4 2451.31  3403.3 2498.43
  3534.5  2512.9    3797 2518.02  3867.7 2511.19  3938.4 2494.02  4029.2 2491.55
#Mann= 3 , 0 , 0
       0      .1       0  2047.1    .045       0  2062.1      .1       0
Bank Sta=2047.1,2062.1
XS Rating Curve= 0 ,0
Exp/Cntr=0.3,0.1

Chan Stop Cuts=-1
Use User Specified Reach Order=0
Composite Channel Slope=5